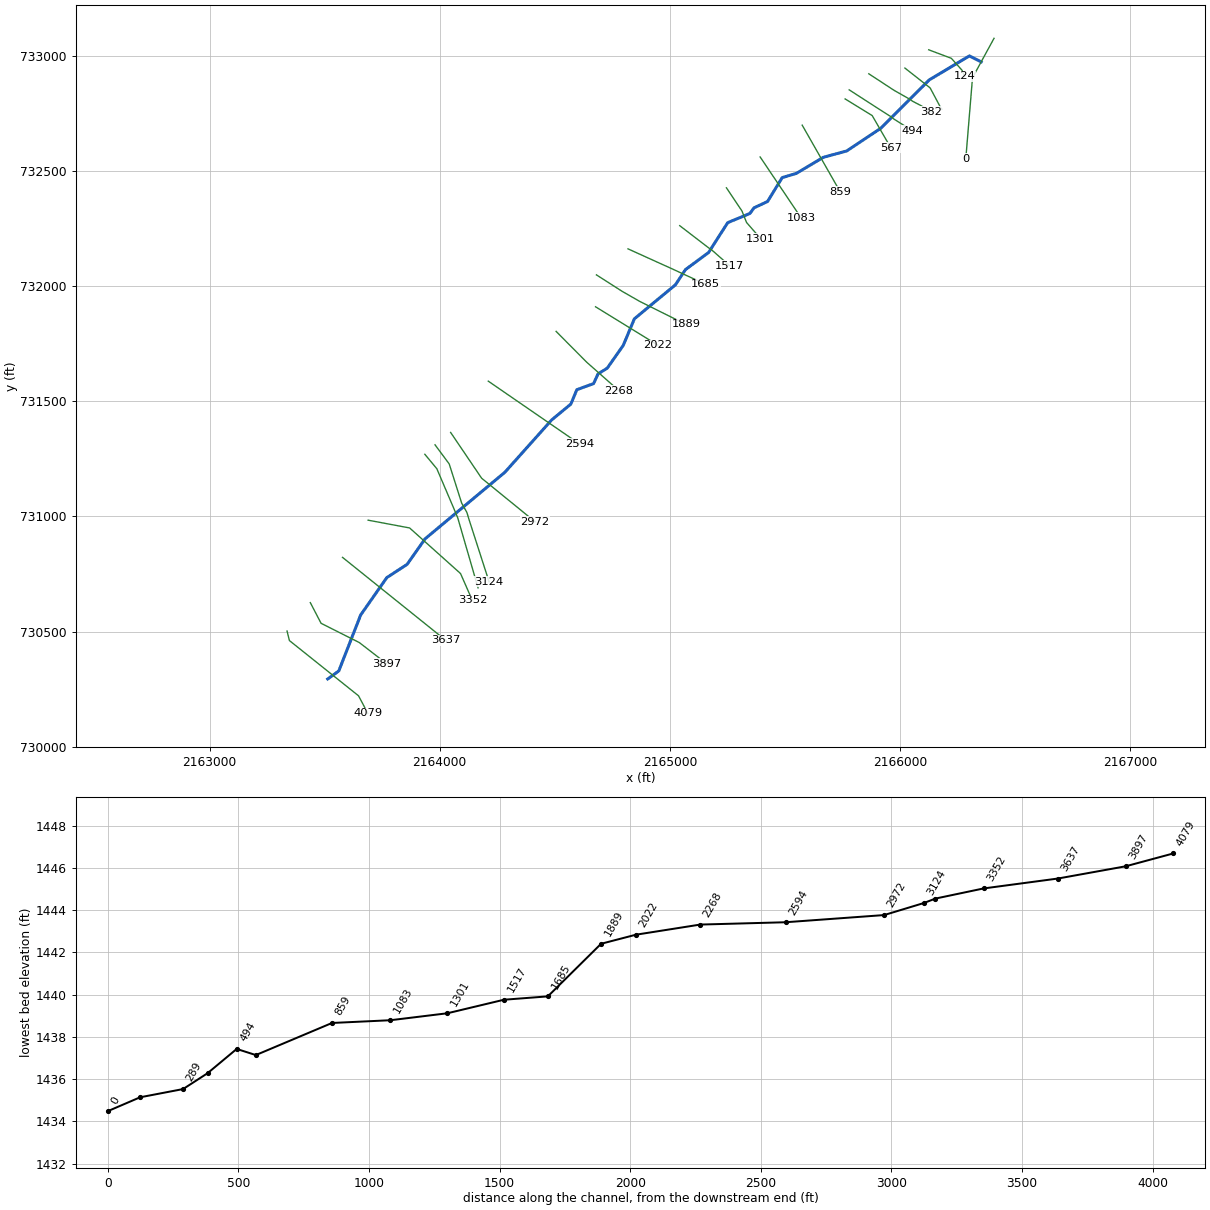
--- SAULSRN.prj (project) ---

Proj Title=SAULSRN
Current Plan=p01
Default Exp/Contr=0,0
English Units
Geom File=g01
Flow File=f01
Plan File=p01
BEGIN DESCRIPTION:
---------- MODELED AS PART OF WVEMD CTP PROGRAM, 2023----------
Stream Name: Sauls Run
Flood Zone:  AFH
Upshur County, WV
HEC-RAS Version: RAS 6.3
Vertical Datum: NAVD88
Projection: NAD 1983 StatePlane West Virginia S FIPS 4702 (US Feet)
Terrain: 1-meter LIDAR (FEMA Region III 3DEP collected 2016-2018)
Land Use: 2019 NLCD
Hydrologic Method:
WV SIR2010-5033 regression equations
Additional Model Notes:
Coincident peak with FINKRN
END DESCRIPTION:
DSS File=dss
DSS Export Rating Curves= 0
DSS Export Rating Curve Sorted= 0
DSS Export Volume Flow Curves= 0
DXF OffsetX= 0
DXF OffsetY= 0
DXF ScaleX= 0
DXF ScaleY= 0

--- SAULSRN.p01 (plan) ---

Plan Title=Floodplain
Program Version=6.30
Short Identifier=Floodplain
Geom File=g01
Flow File=f01
Subcritical Flow
K Sum by GR= 0
Std Step Tol= 0.01
Critical Tol= 0.01
Num of Std Step Trials= 20
Max Error Tol= 0.3
Flow Tol Ratio= 0.001
Split Flow NTrial= 30
Split Flow Tol= 0.02
Split Flow Ratio= 0.02
Log Output Level= 0
Friction Slope Method= 1
Unsteady Friction Slope Method= 2
Unsteady Bridges Friction Slope Method= 1
Parabolic Critical Depth
Global Vel Dist= 0 , 0 , 0
Global Log Level= 0
CheckData=False
Encroach Param=-1 ,0,0, 0
Computation Interval=0.1SEC
Output Interval=1SEC
Instantaneous Interval=Max Profile
Mapping Interval=1HOUR
Computation Time Step Use Courant=        0
Computation Time Step Use Time Series=    0
Computation Time Step Count To Double=0
Computation Time Step Max Doubling=0
Computation Time Step Max Halving=0
Computation Time Step Residence Courant=0
Run HTab= 0
Run UNet= 0
Run Sediment= 0
Run PostProcess= 0
Run WQNet= 0
Run RASMapper=-1
UNET Theta= 0
UNET Theta Warmup= 0
UNET ZTol= 0
UNET ZSATol= 0
UNET MxIter= 0
UNET Max Iter WO Improvement= 0
UNET MaxInSteps= 0
UNET DtIC= 0
UNET DtMin= 0
UNET MaxCRTS= 0
UNET WFStab= 0
UNET SFStab= 0
UNET WFX= 1
UNET SFX= 1
UNET Gravity=32.17405
UNET 1D Methodology=Finite Difference
UNET DSS MLevel= 1
UNET Pardiso=0
UNET DZMax Abort= 0
UNET Use Existing IB Tables= 0
UNET Froude Reduction=False
UNET Froude Limit= 0
UNET Froude Power= 0
UNET D1 Cores= 0
UNET WindReference=Eulerian
UNET WindDragFormulation=Hsu (1988)
UNET D2 Coriolis=0
UNET D2 Cores= 0
UNET D2 Theta= 1
UNET D2 Theta Warmup= 1
UNET D2 Z Tol= 0.01
UNET D2 Volume Tol= 0.01
UNET D2 Max Iterations= 20
UNET D2 Equation= 0
UNET D2 RampUpFraction=0.1
UNET D2 TimeSlices= 1
UNET D2 Turbulence Formulation=Non-Conservative (original)
UNET D2 Eddy Viscosity=0.3
UNET D2 Transverse Eddy Viscosity=0.1
UNET D2 Smagorinsky Mixing=0
UNET D2 BCVolumeCheck=0
UNET D2 Cores=0
UNET D2 SolverType=PARDISO (Direct)
UNET D2 Minimum Iterations= 3
UNET D2 Maximum Iterations= 30
UNET D2 Restart Number= 10
UNET D2 Relaxation Coeff=1.3
UNET D2 SOR Precondition Iterations= 10
UNET D2 ILUT Maximum Fill= 8
UNET D2 ILUT Tolerance=1E-08
UNET D2 Convergence Tolerance=0.00001
UNET D1D2 MaxIter= 0
UNET D1D2 ZTol=0.01
UNET D1D2 QTol=0.1
UNET D1D2 MinQTol=1
DSS File=dss
Write IC File= 0
Write IC File at Fixed DateTime=0
Write IC File at Sim End=0
Echo Input=False
Echo Parameters=False
Echo Output=False
Write Detailed= 0
HDF Write Warmup=0
HDF Write Time Slices=0
HDF Flush=0
HDF Compression= 1
HDF Chunk Size= 1
HDF Spatial Parts= 1
HDF Use Max Rows=0
HDF Fixed Rows= 1
Calibration Method= 0
Calibration Iterations= 20
Calibration Max Change=0.05
Calibration Tolerance=0.2
Calibration Maximum=1.5
Calibration Minimum=0.5
Calibration Optimization Method= 1
WQ AD Non Conservative
WQ ULTIMATE=-1
WQ Max Comp Step=1HOUR
WQ Output Interval=15MIN
WQ Output Selected Increments= 0
WQ Output face flow=0
WQ Output face velocity=0
WQ Output face area=0
WQ Output face dispersion=0
WQ Output cell volume=0
WQ Output cell surface area=0
WQ Output cell continuity=0
WQ Output cumulative cell continuity=0
WQ Output face conc=0
WQ Output face dconc_dx=0
WQ Output face courant=0
WQ Output face peclet=0
WQ Output face adv mass=0
WQ Output face disp mass=0
WQ Output cell mass=0
WQ Output cell source sink temp=0
WQ Output nsm pathways=0
WQ Output nsm derived pathways=0
WQ Create Restart=0
WQ Fixed Restart=0
WQ System Summary=0
WQ Write To DSS=0
Sorting and Armoring Iterations= 10
XS Update Threshold= 0.02
Bed Roughness Predictor= 0
Hydraulics Update Threshold= 0.02
Energy Slope Method= 1
Volume Change Method= 1
Sediment Retention Method= 0
Sediment TS Multiplier= 1
Warm Up Method= 0
XS Weighting Method= 0
Number of US Weighted Cross Sections= 1
Number of DS Weighted Cross Sections= 1
Upstream XS Weight=0
Main XS Weight=1
Downstream XS Weight=0
Number of DS XS's Weighted with US Boundary= 1
Upstream Boundary Weight= 1
Weight of XSs Associated with US Boundary= 0
Number of US XS's Weighted with DS Boundary= 1
Downstream Boundary Weight= 0.5
Weight of XSs Associated with DS Boundary= 0.5
Percentile Method= 0
Sediment Output Level= 3
Mass or Volume Output= 0
Output Increment Type= 1
Profile and TS Output Increment= 1
Transport Output Increment 1
XS Output Flag= 0
XS Output Increment= 10
Read HDF5 Sediment Hotstart= 0
Sediment Hotstart Type= 0
Write Gradation File= 0
Read Gradation Hotstart= 0
Write HDF5 File= 1
Write Binary Output= 1
Write DSS Sediment File= 0
DSS Sediment Output Type= 1
SV Curve= 0
Specific Gage Flag= 0
Subcell Erosion Methods= 0
Subcell Deposition Methods= 0
Advection Scheme= 1
Matrix Solver= 0
Implicit Weighting Factor= 1
Maximum Outer Loop Convergence Iterations= 5
Convergence Maximum Absolute= 0.001
Convergence RMSE= 0.0001
Grain Fractions Max Abs Error= 0.001
Max Subgrid Regions= 1
Max Subgrid Length Scale= 3.402823E+38
Initial Layer Thickness= 3.402823E+38
Min Layer Thickness= 3.402823E+38
Max Layer Thickness= 3.402823E+38
Number of Layers= 5

--- SAULSRN.f01 (steady flow) ---

Flow Title=Flows
Program Version=6.30
Number of Profiles= 1
Profile Names=01pct
River Rch & RM=SAULSRN,Main,4079
     371
Boundary for River Rch & Prof#=SAULSRN,Main            , 1
Up Type= 0
Dn Type= 1
Dn Known WS=1440.58
DSS Import GetInterval= 0
DSS Import GetPeak= 0
DSS Import FillOption= 0

--- SAULSRN.g01 (geometry) ---

Geom Title=Geometry
Program Version=6.30

River Reach=SAULSRN         ,Main
Reach XY= 30
2163513.33721283730293.7705779222163561.45440026730328.614913642
2163656.55100001730571.913000003     2163770.101 730734.28200002
2163858.32500002730791.8300000132163936.24700001730902.547000006
2164283.16400005731192.0010000022164486.11100003731419.044000015
2164569.90000002731488.3530000152164595.88399999731550.821999997
2164668.77000001731577.4070000052164687.80000003731619.359000012
2164727.94800001731644.3690000182164797.45800005731743.239000008
2164845.96199998731858.906000018     2165024.243732006.567000002
2165067.76799999732072.5849999932165168.38300003732146.959000006
2165251.51400001732276.7060000152165347.86500002732316.540000021
     2165365.836      732340.9782165424.70000002732368.821999997
2165488.28600001732472.4420000172165549.78299999732490.785000011
2165666.90900002732560.608999997     2165768.583732588.252000019
     2165916.759732686.7780000122166127.17500001732896.966000006
     2166301.592      733001.2442166352.81741099732975.328915504

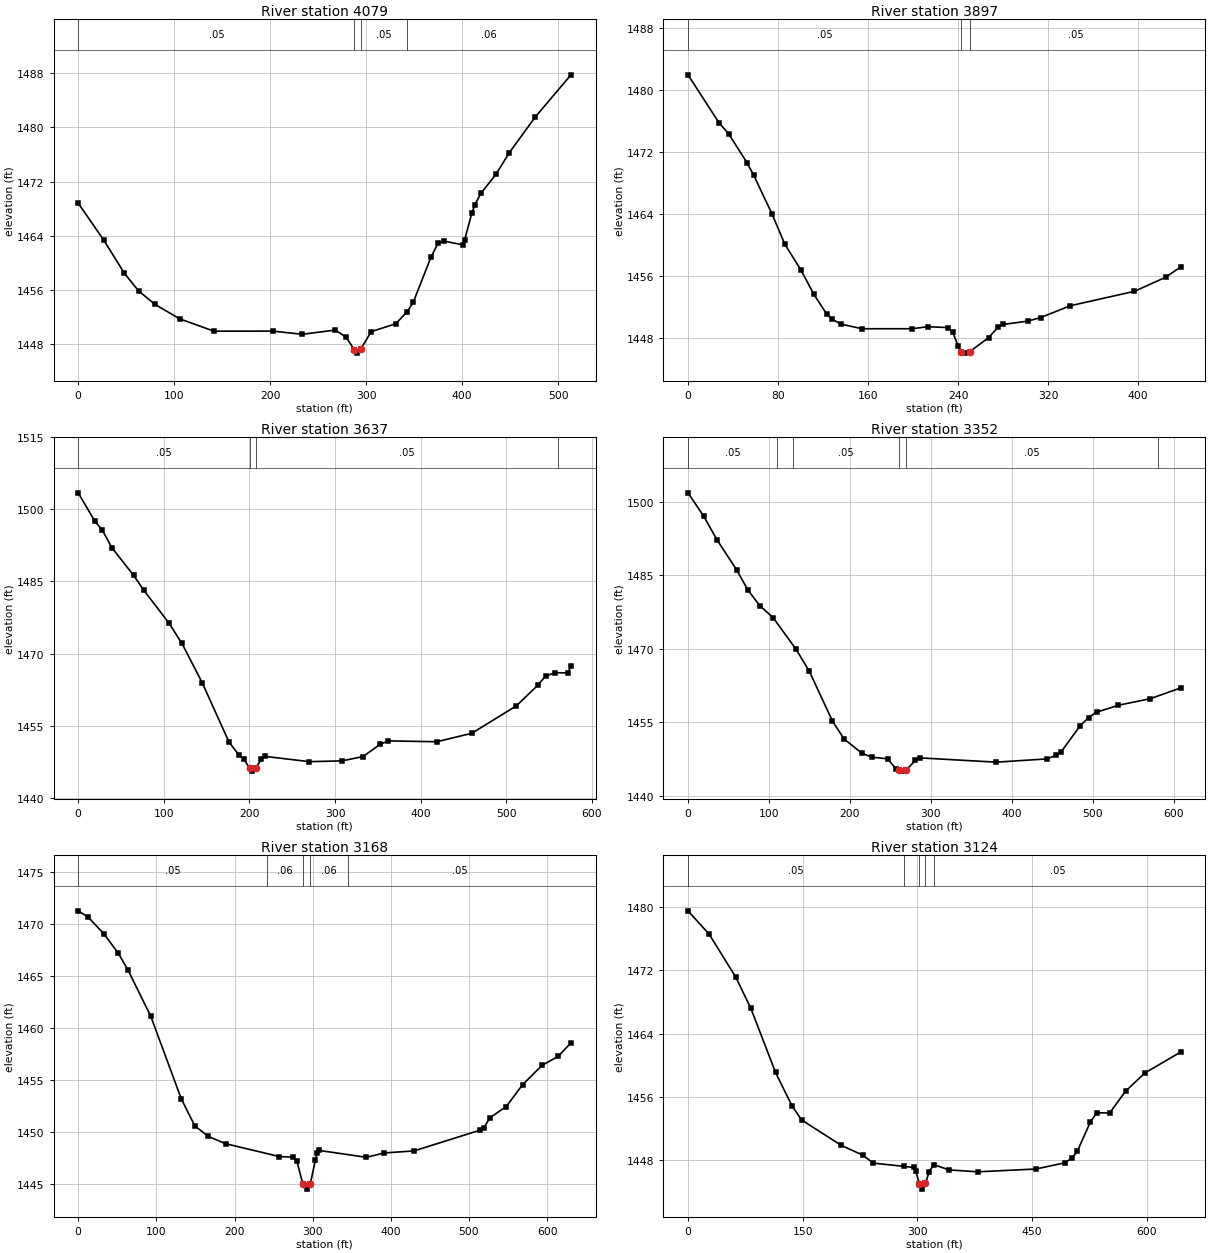
Type RM Length L Ch R = 1 ,4079    ,182.7,182.7,182.7
XS GIS Cut Line= 4
2163336.67023472  730501.99136472163346.87835679730460.764851462
2163647.21327533730220.7639933432163687.81847421730144.330677801
#Sta/Elev= 30
       0 1468.81    26.7 1463.35    48.2 1458.46      63 1455.86    80.1 1453.87
   105.6 1451.76   141.4 1449.93   202.5 1449.94   233.6 1449.47   267.9 1450.09
   278.9 1449.08   287.9 1447.17   290.7 1446.69   294.31447.238   305.3 1449.86
   330.9 1451.02     343 1452.83   349.4 1454.28   367.5 1460.81     375  1462.9
   381.4  1463.2   400.6 1462.68   402.6 1463.34   410.2 1467.36   413.4  1468.6
   419.8 1470.29   435.5 1473.09   449.1 1476.23   476.3 1481.52   513.5 1487.74
#Mann= 4 ,-1,0
       0     .05       0   287.9    .045       0   294.3     .05       0
  342.47     .06       0
Bank Sta=287.9,294.3
XS Rating Curve= 0 ,0
Exp/Cntr(USF)=0,0
Exp/Cntr=0.3,0.1

Type RM Length L Ch R = 1 ,3897    ,261.1,259.6,257.6
XS GIS Cut Line= 4
2163437.74955934730625.5661344492163484.54723252730535.670524318
 2163650.7812365  730452.02259432163769.80931847730359.933617301
#Sta/Elev= 30
       0 1482.01    27.5 1475.84    36.5 1474.32    52.5 1470.65    58.4 1469.05
    74.6 1464.07    86.1 1460.13   100.5 1456.78   111.9 1453.65   123.3 1451.13
   127.8  1450.5   135.7 1449.83   154.7 1449.23   199.4 1449.23   212.9 1449.49
   230.8 1449.38   235.3 1448.77     240 1447.02   242.9 1446.27   245.9 1446.08
   250.61446.288   267.1 1448.08   275.6 1449.43     280 1449.78   301.9 1450.21
   313.3 1450.67   339.8  1452.2   396.7 1454.06   424.5 1455.88   437.9 1457.22
#Mann= 3 ,-1,0
       0     .05       0   242.9    .045       0   250.6     .05       0
Bank Sta=242.9,250.6
XS Rating Curve= 0 ,0
Exp/Cntr(USF)=0,0
Exp/Cntr=0.3,0.1

Type RM Length L Ch R = 1 ,3637    ,284.3,284.7,284.3
XS GIS Cut Line= 2
2163577.69338854730822.2278222322164026.32831104 730461.80445352
#Sta/Elev= 30
       0 1503.47    19.6 1497.51    28.1 1495.73    39.5    1492    64.8 1486.27
    76.5 1483.21   105.8 1476.39   121.2 1472.09   144.8 1463.93   176.1 1451.57
   187.4 1448.93   193.3 1448.09   200.21446.083   203.3  1445.5   207.4 1446.08
   213.6 1447.94   218.7 1448.56     270 1447.47   308.2 1447.64   332.6 1448.53
   352.9 1451.11   362.3  1451.8   418.8 1451.62   459.8 1453.39   511.8 1459.11
   536.8 1463.41   545.9 1465.32   557.3    1466   571.5 1465.96   575.5 1467.32
#Mann= 4 ,-1,0
       0     .05       0   200.2    .045       0   207.4     .05       0
     560     .07       0
Bank Sta=200.2,207.4
XS Rating Curve= 0 ,0
Exp/Cntr(USF)=0,0
Exp/Cntr=0.3,0.1

Type RM Length L Ch R = 1 ,3352    ,190.1,184.4,178.4
XS GIS Cut Line= 4
2163688.94942822730983.8697884492163869.32422527730950.041791939
2164090.47789787730752.0227764182164141.99114667730634.836866775
#Sta/Elev= 30
       0 1501.83    19.6 1497.02    35.8 1492.25    60.3 1486.05    73.6 1482.09
    88.7 1478.78     105 1476.38   133.5 1469.88   149.8 1465.41   178.3 1455.27
   192.7  1451.6   214.5 1448.71   226.8 1447.87   246.4 1447.55   256.8 1445.49
   260.4  1445.2   265.5 1445.03   268.8 1445.16   280.8 1447.23   286.8 1447.73
   380.6 1446.86   442.7 1447.52   454.7 1448.26   460.9    1449   483.8  1454.2
   494.5 1455.97   504.5 1457.06   531.5 1458.48   570.9 1459.82   608.4 1462.02
#Mann= 6 ,-1,0
       0     .05       0     110      .1       0     130     .05       0
   260.4    .045       0   268.8     .05       0  580.37     .06       0
Bank Sta=260.4,268.8
XS Rating Curve= 0 ,0
Exp/Cntr(USF)=0,0
Exp/Cntr=0.3,0.1

Type RM Length L Ch R = 1 ,3168    ,42.3,44,45.7
XS GIS Cut Line= 5
2163935.36580892731270.201278754 2163987.5598554731207.391494007
2164061.16050238731035.0796941482164078.71988666730992.833056718
2164166.63829515730689.651066703
#Sta/Elev= 30
       0  1471.3    12.7  1470.7    32.5 1469.12    51.3 1467.23    63.9 1465.58
    92.8 1461.18   131.9 1453.23   149.3 1450.62   166.7 1449.61   188.5 1448.92
   257.5 1447.68   275.4 1447.62   279.8 1447.24   287.3 1445.08   292.8 1444.55
   297.1 1445.09   303.4 1447.31   305.8 1447.99   308.2 1448.27   368.6 1447.61
   391.8 1448.03   429.5 1448.22   514.3 1450.22   519.1 1450.46   526.8 1451.41
   547.7 1452.49   568.5 1454.58   593.5 1456.45   614.3 1457.32   630.5 1458.62
#Mann= 5 ,-1,0
       0     .05       0  241.67     .06       0   287.3    .045       0
   297.1     .06       0  344.79     .05       0
Bank Sta=287.3,297.1
XS Rating Curve= 0 ,0
Exp/Cntr(USF)=0,0
Exp/Cntr=0.3,0.1

Type RM Length L Ch R = 1 ,3124    ,146.8,152,156.2
XS GIS Cut Line= 6
2163979.62613561731311.2936410872164041.33237405731228.157483108
2164095.43925401731057.9867545862164118.00159487731017.808595223
2164127.83098215730985.3716171852164214.42714125730716.559889173
#Sta/Elev= 30
       0 1479.51    27.8 1476.54    62.4 1471.15    82.3 1467.17   114.5 1459.09
     136 1454.87   148.6 1453.08   200.5 1449.87   229.2 1448.61   241.9 1447.63
   282.1 1447.22     295 1447.08   297.9 1446.59   302.6 1445.04     306 1444.34
   310.6 1445.06   315.5 1446.56   321.4 1447.44   341.4 1446.77   379.1 1446.53
   454.8 1446.88   492.6 1447.66   502.4 1448.27   509.4 1449.17   526.2 1452.81
   534.6    1454   551.4 1453.95   572.4 1456.73   597.7 1459.03   644.5 1461.67
#Mann= 5 ,-1,0
       0     .05       0   282.1     .06       0   302.6    .045       0
   310.6     .06       0   322.1     .05       0
Bank Sta=302.6,310.6
XS Rating Curve= 0 ,0
Exp/Cntr(USF)=0,0
Exp/Cntr=0.3,0.1

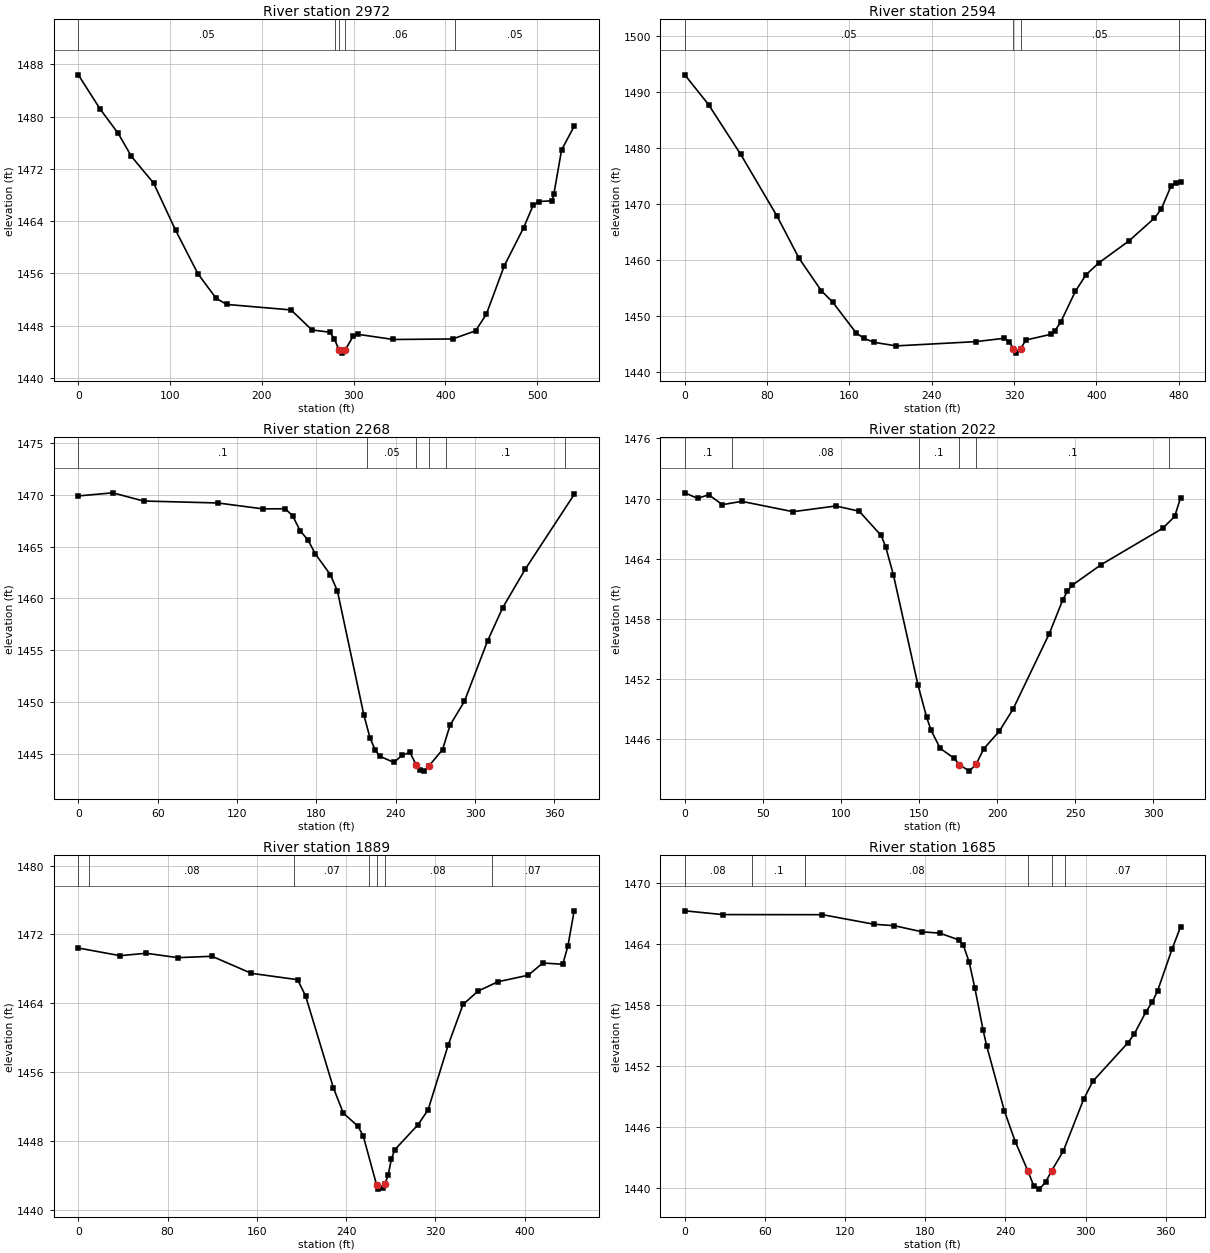
Type RM Length L Ch R = 1 ,2972    ,375.2,377.4,377.2
XS GIS Cut Line= 3
2164047.49457327731365.0785994622164182.06257724731166.281869789
2164414.82903353730976.748651475
#Sta/Elev= 30
       0 1486.41      24 1481.11    43.4 1477.45    57.8 1473.92      82 1469.82
   106.1 1462.56   130.3 1455.93   150.2 1452.16   161.7 1451.23   231.7 1450.39
   254.5 1447.32   273.7 1446.98   278.9 1446.01   284.1 1444.18   287.8 1443.77
   290.51444.189   299.5 1446.38   304.7 1446.65   343.2 1445.86   407.9 1445.94
   432.8 1447.19   444.5 1449.72   464.1 1457.16   485.2    1463   495.5 1466.42
   501.5 1466.99   516.2 1467.12   518.1 1468.14   526.5 1474.91   540.2 1478.52
#Mann= 5 ,-1,0
       0     .05       0  280.06     .06       0   284.1    .045       0
   290.5     .06       0  410.06     .05       0
Bank Sta=284.1,290.5
XS Rating Curve= 0 ,0
Exp/Cntr(USF)=0,0
Exp/Cntr=0.3,0.1

Type RM Length L Ch R = 1 ,2594    ,325.7,326.3,321.9
XS GIS Cut Line= 2
2164210.92089868731588.0271514842164607.99907063731314.750945706
#Sta/Elev= 30
       0 1493.03    23.1 1487.72    54.4 1478.84    89.7 1467.84   110.9 1460.38
   132.6 1454.58   143.9 1452.49   166.6 1447.02   174.4 1446.04   184.2 1445.35
   205.5 1444.72   283.2 1445.48   310.7 1446.08   315.5  1445.5   319.3 1444.25
   322.2 1443.43   326.51444.252   331.7 1445.77     356 1446.79   359.6 1447.37
   365.4 1448.95   379.7 1454.45     390 1457.39   402.7 1459.55   431.5 1463.39
   456.6  1467.5   463.2 1469.12   472.5 1473.13   477.5 1473.75     482  1473.9
#Mann= 4 ,-1,0
       0     .05       0   319.3    .045       0   326.5     .05       0
     480     .06       0
Bank Sta=319.3,326.5
XS Rating Curve= 0 ,0
Exp/Cntr(USF)=0,0
Exp/Cntr=0.3,0.1

Type RM Length L Ch R = 1 ,2268    ,243.9,246.3,247.3
XS GIS Cut Line= 3
 2164505.8545679731804.153503954 2164638.4967458731670.536477737
2164778.33483806 731546.94248444
#Sta/Elev= 30
       0  1469.9      26  1470.2    49.3 1469.41   105.5 1469.22   139.6 1468.65
   156.4 1468.66     162 1467.99   167.8 1466.52   173.6 1465.65   179.3 1464.28
   190.5 1462.31   195.9 1460.72   215.9 1448.74   220.5 1446.55   224.4 1445.37
   227.9 1444.76   238.6 1444.16   244.7 1444.84   250.7 1445.14   255.6 1443.89
   258.4 1443.41   261.3 1443.32   265.3 1443.85   275.4  1445.4   281.1 1447.77
   291.9 1450.05   309.4 1455.89   320.8 1459.09   337.8  1462.8   374.9 1470.04
#Mann= 6 ,-1,0
       0      .1       0  218.27     .05       0   255.6    .045       0
   265.3     .05       0  278.27      .1       0  368.27     .05       0
Bank Sta=255.6,265.3
XS Rating Curve= 0 ,0
Exp/Cntr(USF)=0,0
Exp/Cntr=0.3,0.1

Type RM Length L Ch R = 1 ,2022    ,130,133.4,133.1
XS GIS Cut Line= 2
2164677.14935362731911.1499610672164947.45108466731744.735212898
#Sta/Elev= 30
       0 1470.57     8.3 1470.01    15.3 1470.39      24 1469.39    36.4 1469.72
    69.3 1468.69    96.7 1469.26   111.6 1468.74   125.7 1466.32   128.6 1465.19
   133.5 1462.42   149.2 1451.47   154.8 1448.21   157.7 1446.89   163.5 1445.11
   172.3 1444.13   175.71443.491   182.1 1442.84   186.41443.501   191.4 1445.07
   201.3 1446.81   210.1 1449.01   233.3 1456.53     242 1459.92   244.9 1460.76
   247.8 1461.34   266.6 1463.42     306 1467.04   313.6 1468.22   317.4 1470.09
#Mann= 6 ,-1,0
       0      .1       0      30     .08       0     150      .1       0
   175.7    .045       0   186.4      .1       0     310     .06       0
Bank Sta=175.7,186.4
XS Rating Curve= 0 ,0
Exp/Cntr(USF)=0,0
Exp/Cntr=0.3,0.1

Type RM Length L Ch R = 1 ,1889    ,203.5,203.7,204.9
XS GIS Cut Line= 4
2164681.08474871732049.7834171662164793.42027847731977.823685116
2164868.94183033731934.6247265752165069.34366262731834.791385528
#Sta/Elev= 30
       0 1470.42    37.4 1469.53    60.7 1469.81    89.2  1469.3   119.8 1469.46
     155 1467.48   196.5 1466.74   203.7 1464.83   228.5  1454.2   237.4 1451.25
   250.6 1449.71   255.3 1448.59   267.21442.932   268.6 1442.41   273.2 1442.51
   274.6 1442.97   277.6 1444.03   280.6 1445.95   283.6 1446.99   304.5 1449.91
   313.4 1451.62   331.3  1459.1   344.7 1463.86   358.1 1465.41     376  1466.5
   403.1 1467.26   416.2 1468.68   434.1 1468.53   438.7 1470.66   444.3 1474.74
#Mann= 7 ,-1,0
       0      .1       0      10     .08       0  193.41     .07       0
  260.41     .08       0   267.2    .045       0   274.6     .08       0
  370.41     .07       0
Bank Sta=267.2,274.6
XS Rating Curve= 0 ,0
Exp/Cntr(USF)=0,0
Exp/Cntr=0.3,0.1

Type RM Length L Ch R = 1 ,1685    ,169.2,168.2,162.3
XS GIS Cut Line= 4
2164818.35074596732162.7852122552164922.86076949732115.354206824
2165013.74419601732074.2579336872165155.91615669732008.532425097
#Sta/Elev= 30
       0 1467.29    28.4 1466.92     103 1466.91   141.6 1465.97   156.7 1465.83
   177.7 1465.22   190.8  1465.1   205.1 1464.43   208.4 1463.93   212.8 1462.27
   217.1  1459.7   223.2  1455.6     226 1453.98   239.2 1447.61   247.3  1444.6
   256.9 1441.67   261.3  1440.2   265.4 1439.92   270.1 1440.62   274.6 1441.73
   283.3 1443.67   298.5 1448.75   305.3 1450.51   331.7 1454.32   336.2 1455.13
     345 1457.32   349.8  1458.3   353.8  1459.4   364.8 1463.57   371.1 1465.73
#Mann= 6 ,-1,0
       0     .08       0      50      .1       0      90     .08       0
   256.9    .045       0   274.6     .08       0  284.51     .07       0
Bank Sta=256.9,274.6
XS Rating Curve= 0 ,0
Exp/Cntr(USF)=0,0
Exp/Cntr=0.3,0.1

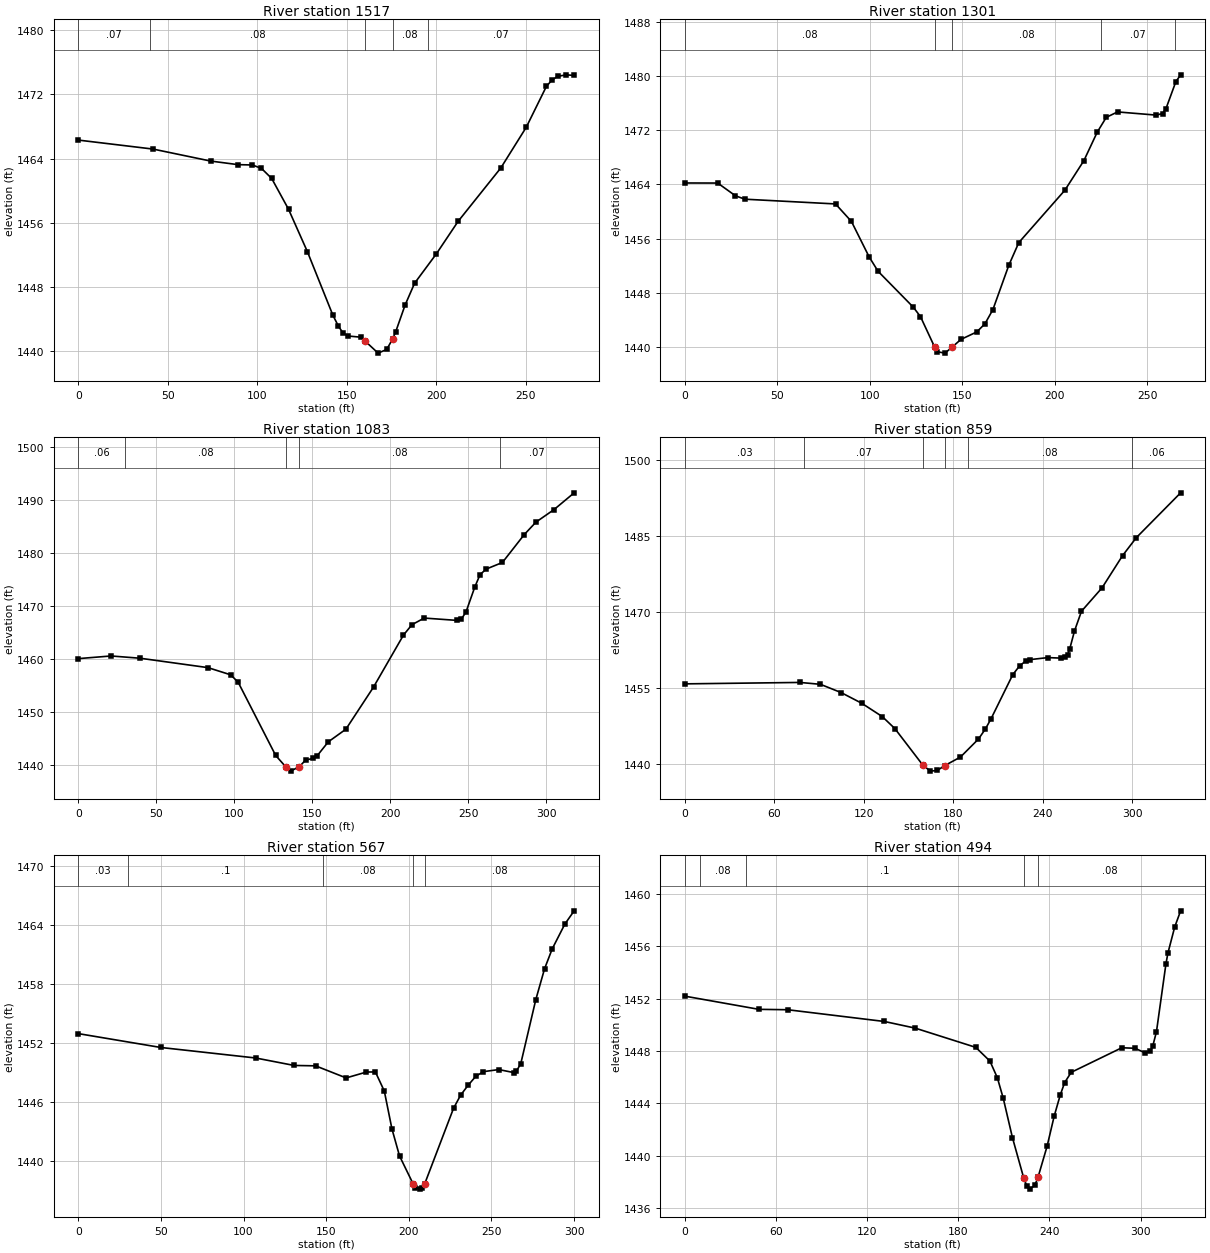
Type RM Length L Ch R = 1 ,1517    ,222.2,216.2,207.2
XS GIS Cut Line= 4
2165042.99361457732263.5491720292165170.30190238 732165.83450302
2165182.75661608732157.4740907732165259.12690702 732090.36485169
#Sta/Elev= 30
       0  1466.3    41.8 1465.18    73.9 1463.69    89.3 1463.24    97.3  1463.2
   102.4 1462.77   108.1 1461.52   117.5 1457.69   128.1 1452.38   142.3 1444.49
   145.4 1443.12     148 1442.26   150.9 1441.89   157.8 1441.75   160.51441.226
   167.6 1439.76   172.4 1440.22   175.71441.515   177.4  1442.4   182.7 1445.76
     188 1448.47   200.2 1452.14   212.3 1456.17   236.2 1462.83   250.4 1467.89
   261.7    1473   264.6 1473.73   267.9 1474.24   272.9 1474.43   277.2 1474.35
#Mann= 5 ,-1,0
       0     .07       0      40     .08       0   160.5    .045       0
   175.7     .08       0  195.49     .07       0
Bank Sta=160.5,175.7
XS Rating Curve= 0 ,0
Exp/Cntr(USF)=0,0
Exp/Cntr=0.3,0.1

Type RM Length L Ch R = 1 ,1301    ,214.1,218,218.4
XS GIS Cut Line= 4
2165245.91550791732427.9680999112165313.52358891732327.214759466
2165333.23714285732277.5091119592165394.60622683732207.249877876
#Sta/Elev= 30
       0 1464.21    17.8  1464.2    27.4 1462.32    32.5 1461.82    81.5 1461.12
    90.1 1458.54    99.7  1453.3   104.5 1451.19   123.5 1445.91   127.4 1444.52
  135.15 1439.98   136.4 1439.33   140.7 1439.12  144.56 1440.01   149.3 1441.14
   157.9 1442.25   162.3 1443.45   166.6 1445.54   175.2 1452.08   180.6 1455.42
   205.5 1463.14   215.8 1467.51     223  1471.7   227.9 1473.89     234 1474.69
   254.9 1474.22   258.3 1474.45   260.2 1475.19   265.5 1479.14   268.1 1480.16
#Mann= 5 ,-1,0
       0     .08       0  135.15    .045       0  144.56     .08       0
  224.81     .07       0  264.81     .06       0
Bank Sta=135.15,144.56
XS Rating Curve= 0 ,0
Exp/Cntr(USF)=0,0
Exp/Cntr=0.3,0.1

Type RM Length L Ch R = 1 ,1083    ,223.1,223.8,221.3
XS GIS Cut Line= 2
2165392.45758589732562.1415809832165569.80958042732298.455325645
#Sta/Elev= 30
       0 1460.01      21 1460.51    39.7 1460.08    83.1 1458.31    97.6 1456.96
   102.4 1455.58   126.5 1441.74   133.1 1439.55   136.1 1438.79   141.7 1439.65
   145.8 1440.91   150.6 1441.18   153.2 1441.73   160.2 1444.31   171.5  1446.7
   189.2 1454.64   208.4 1464.45   213.8  1466.4   221.7 1467.66   242.6 1467.22
   245.5 1467.48   248.4 1468.75   254.1  1473.5   257.5 1475.87   261.5 1476.91
   271.8 1478.14   285.8  1483.4   293.3 1485.75   304.9 1488.12   317.8 1491.28
#Mann= 5 ,-1,0
       0     .06       0      30     .08       0   133.1    .045       0
   141.7     .08       0     270     .07       0
Bank Sta=133.1,141.7
XS Rating Curve= 0 ,0
Exp/Cntr(USF)=0,0
Exp/Cntr=0.3,0.1

Type RM Length L Ch R = 1 ,859     ,290.3,291.5,290.6
XS GIS Cut Line= 2
2165575.17029031732700.3111143842165739.91010437732411.334711476
#Sta/Elev= 30
       0 1455.84    77.3 1456.12      91 1455.75   104.9 1454.12   118.7 1452.02
   132.5 1449.39   140.9 1447.04   159.81439.796   164.8 1438.66   169.4  1438.8
   174.31439.736   184.9 1441.43     197 1444.98   201.6 1446.94   205.4 1448.95
     220 1457.65   224.6 1459.39   228.8 1460.37   231.8 1460.62   243.5 1461.01
   252.4 1460.91   255.2 1461.08   256.8 1461.54   258.2  1462.7   261.4 1466.25
   266.1 1470.14   279.9 1474.75   293.7 1481.11   302.9 1484.63   332.6 1493.45
#Mann= 6 ,-1,0
       0     .03       0      80     .07       0   159.8    .045       0
   174.3     .07       0     190     .08       0     300     .06       0
Bank Sta=159.8,174.3
XS Rating Curve= 0 ,0
Exp/Cntr(USF)=0,0
Exp/Cntr=0.3,0.1

Type RM Length L Ch R = 1 ,567     ,69.7,73.3,77.8
XS GIS Cut Line= 3
2165761.68329644 732814.291091692165879.30916418732741.972965595
2165960.34031752732601.693227024
#Sta/Elev= 30
       0 1452.97    49.9 1451.56   107.3 1450.49   130.6 1449.73   143.6 1449.69
   162.1 1448.46   174.4 1449.06   179.8 1449.07   185.2 1447.12   189.8 1443.28
   194.4 1440.52   202.71437.652   203.7 1437.28   206.6 1437.14   208.3 1437.21
   209.6 1437.66   227.1 1445.37   231.4 1446.71   235.9 1447.71   240.6 1448.63
   245.2  1449.1   254.5 1449.31   263.7    1449   265.2 1449.16   267.8 1449.92
   276.9 1456.44   282.2 1459.58   286.8 1461.59   294.5 1464.13   300.1 1465.47
#Mann= 5 ,-1,0
       0     .03       0      30      .1       0  148.08     .08       0
   202.7    .045       0   209.6     .08       0
Bank Sta=202.7,209.6
XS Rating Curve= 0 ,0
Exp/Cntr(USF)=0,0
Exp/Cntr=0.3,0.1

Type RM Length L Ch R = 1 ,494     ,109.9,111.6,113
XS GIS Cut Line= 5
2165779.21490263  732853.88503132165899.83403954732776.013128271
 2165966.7985492732733.1429232322165971.89848406732728.042988369
 2166053.0395995732676.644615656
#Sta/Elev= 30
       0  1452.2    48.8 1451.19    67.7 1451.16   131.4 1450.26   151.7 1449.75
   191.5 1448.28   200.8 1447.23   205.7 1445.95   209.6 1444.37   215.6 1441.38
     223  1438.3     225 1437.69   226.9 1437.43   230.3 1437.71   232.51438.359
   238.4  1440.7   243.1 1443.02   247.1 1444.64     250 1445.59   254.3 1446.37
   287.6 1448.25   296.3 1448.21   302.9 1447.86   306.4 1448.01   307.9 1448.35
   310.4 1449.48   316.6 1454.64   317.9 1455.48   322.4 1457.49   326.3 1458.73
#Mann= 5 ,-1,0
       0      .1       0      10     .08       0      40      .1       0
     223    .045       0   232.5     .08       0
Bank Sta=223,232.5
XS Rating Curve= 0 ,0
Exp/Cntr(USF)=0,0
Exp/Cntr=0.3,0.1

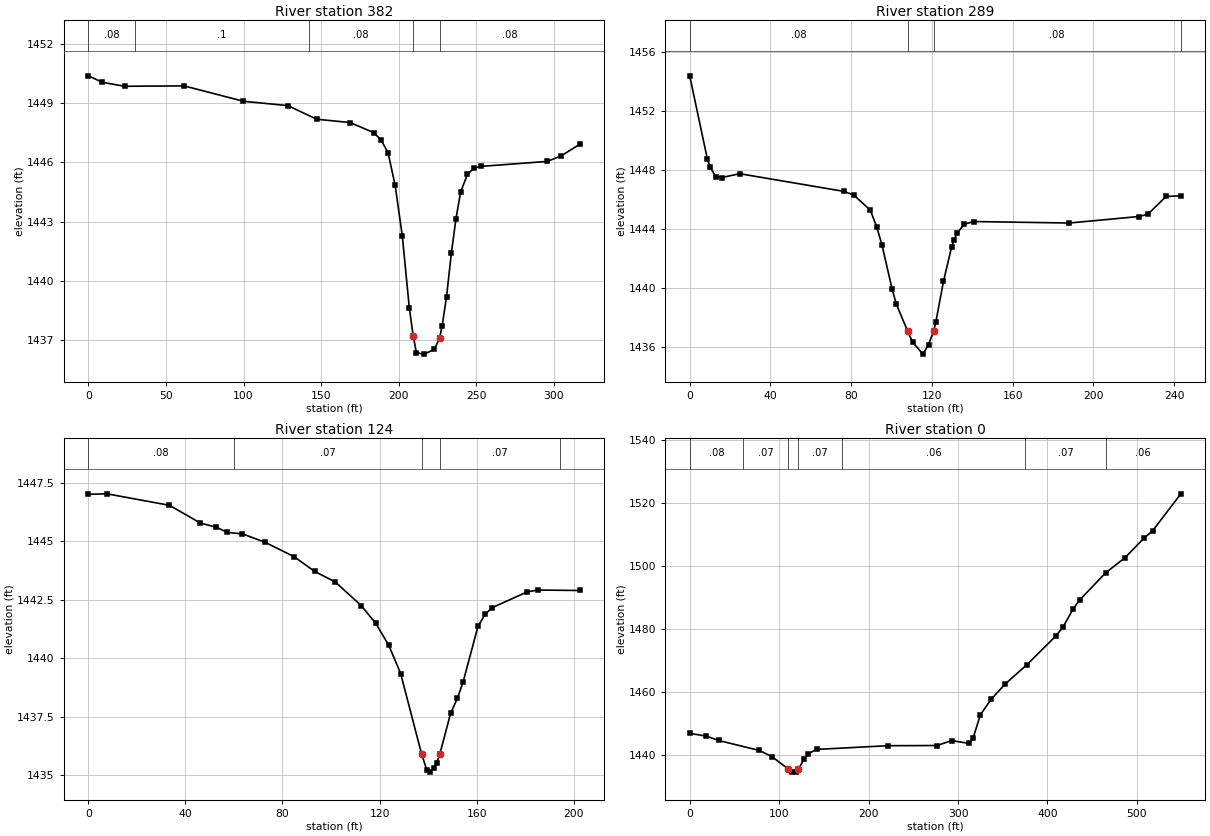
Type RM Length L Ch R = 1 ,382     ,95.1,93.7,91.9
XS GIS Cut Line= 6
2165864.59023071732923.5619361492165975.07132492732851.250413658
2166045.35760276732811.4735860012166053.55392665732804.916526891
2166092.78127142732784.5076604922166134.46067838732758.684355236
#Sta/Elev= 30
       0 1450.39     9.1 1450.06    23.4 1449.86    61.7 1449.88    99.9  1449.1
   128.6 1448.88   147.1 1448.19   168.7 1448.02   183.9 1447.51   188.5 1447.15
   193.1  1446.5   197.7 1444.83   202.3 1442.28   206.8 1438.64   209.3 1437.22
   211.4 1436.35   216.4 1436.28   222.9 1436.52   226.3 1437.08     228 1437.73
   230.8 1439.18   233.9 1441.39   236.9 1443.15   239.9  1444.5   244.3  1445.4
   248.7 1445.72   253.3  1445.8   295.6 1446.05   304.4 1446.32   316.5 1446.91
#Mann= 5 ,-1,0
       0     .08       0      30      .1       0  142.04     .08       0
   209.3    .045       0   226.3     .08       0
Bank Sta=209.3,226.3
XS Rating Curve= 0 ,0
Exp/Cntr(USF)=0,0
Exp/Cntr=0.3,0.1

Type RM Length L Ch R = 1 ,289     ,166.4,164.6,162.2
XS GIS Cut Line= 3
 2166021.3315082732948.4717111932166131.11565143732862.212741512
2166179.90860398732770.725955488
#Sta/Elev= 30
       0 1454.38     8.7 1448.78    10.1 1448.21    12.9 1447.54    15.8 1447.49
    24.8 1447.75    76.5 1446.55    81.3  1446.3    89.5 1445.28    92.7 1444.12
    95.2 1442.95   100.3 1439.92   102.4  1438.9  108.02 1437.07   110.4 1436.35
   115.5 1435.53   118.3 1436.17   120.9 1437.12   121.9 1437.69   125.7 1440.45
   129.7 1442.76   130.8 1443.24   132.6 1443.73   135.9 1444.33   140.8 1444.51
   188.1 1444.41   222.4 1444.85   226.9    1445     236 1446.21   243.3 1446.25
#Mann= 4 ,-1,0
       0     .08       0  108.02    .045       0   120.9     .08       0
   243.3     .07       0
Bank Sta=108.02,120.9
XS Rating Curve= 0 ,0
Exp/Cntr(USF)=0,0
Exp/Cntr=0.3,0.1

Type RM Length L Ch R = 1 ,124     ,,124.1,
XS GIS Cut Line= 4
2166124.96336213733027.8078414952166223.27035632732990.747444351
2166269.40961503732939.2657632052166280.69283819732913.371690985
#Sta/Elev= 30
       0 1447.01     7.7 1447.03    33.4 1446.54    46.2 1445.78    52.8  1445.6
    57.3 1445.38    63.5 1445.32    72.8 1444.96    84.7 1444.35    93.2 1443.72
   101.8 1443.26   112.5 1442.25   118.4  1441.5   123.8 1440.56   128.7 1439.35
   137.31435.924   139.4 1435.25   140.8 1435.14   142.4 1435.31   143.6 1435.55
   144.8  1435.9   149.3 1437.66   152.1  1438.3   154.4 1438.98   160.6 1441.38
   163.5 1441.88   166.3 1442.16   180.8 1442.84   185.2 1442.92   202.4  1442.9
#Mann= 5 ,-1,0
       0     .08       0      60     .07       0   137.3    .045       0
   144.8     .07       0  194.19     .06       0
#XS Ineff= 2 , 0
                          326.89         1444.14
Permanent Ineff=
       F       F
Bank Sta=137.3,144.8
XS Rating Curve= 0 ,0
Exp/Cntr(USF)=0,0
Exp/Cntr=0.3,0.1

Type RM Length L Ch R = 1 ,0       ,124.6,126,124.9
XS GIS Cut Line= 3
2166408.71062563733077.6193648572166315.15248127732906.398140807
2166285.95683105732553.609821486
#Sta/Elev= 30
       0 1446.78    18.7 1445.92    32.4 1444.53      78 1441.35    92.1 1439.37
   110.41435.448   114.5 1434.63   118.6 1434.48   121.6 1435.42   128.1 1438.73
   132.7 1440.32   141.8 1441.69   221.2 1442.87   276.6 1442.93   292.7 1444.49
   312.7 1443.59   316.7 1445.18     325 1452.69   336.8 1457.55   352.9 1462.53
     377  1468.6   409.1 1477.65   417.1 1480.44   428.8 1486.34   436.2 1489.24
   465.3 1497.85   486.4 1502.52   508.2 1508.88   517.4  1511.1   549.1 1522.87
#Mann= 7 ,-1,0
       0     .08       0      60     .07       0   110.4    .045       0
   121.6     .07       0     170     .06       0  375.11     .07       0
  465.11     .06       0
Bank Sta=110.4,121.6
XS Rating Curve= 0 ,0
Exp/Cntr=0.3,0.1
LCMann Table=0

Chan Stop Cuts=-1
Use User Specified Reach Order=0
Composite Channel Slope=5